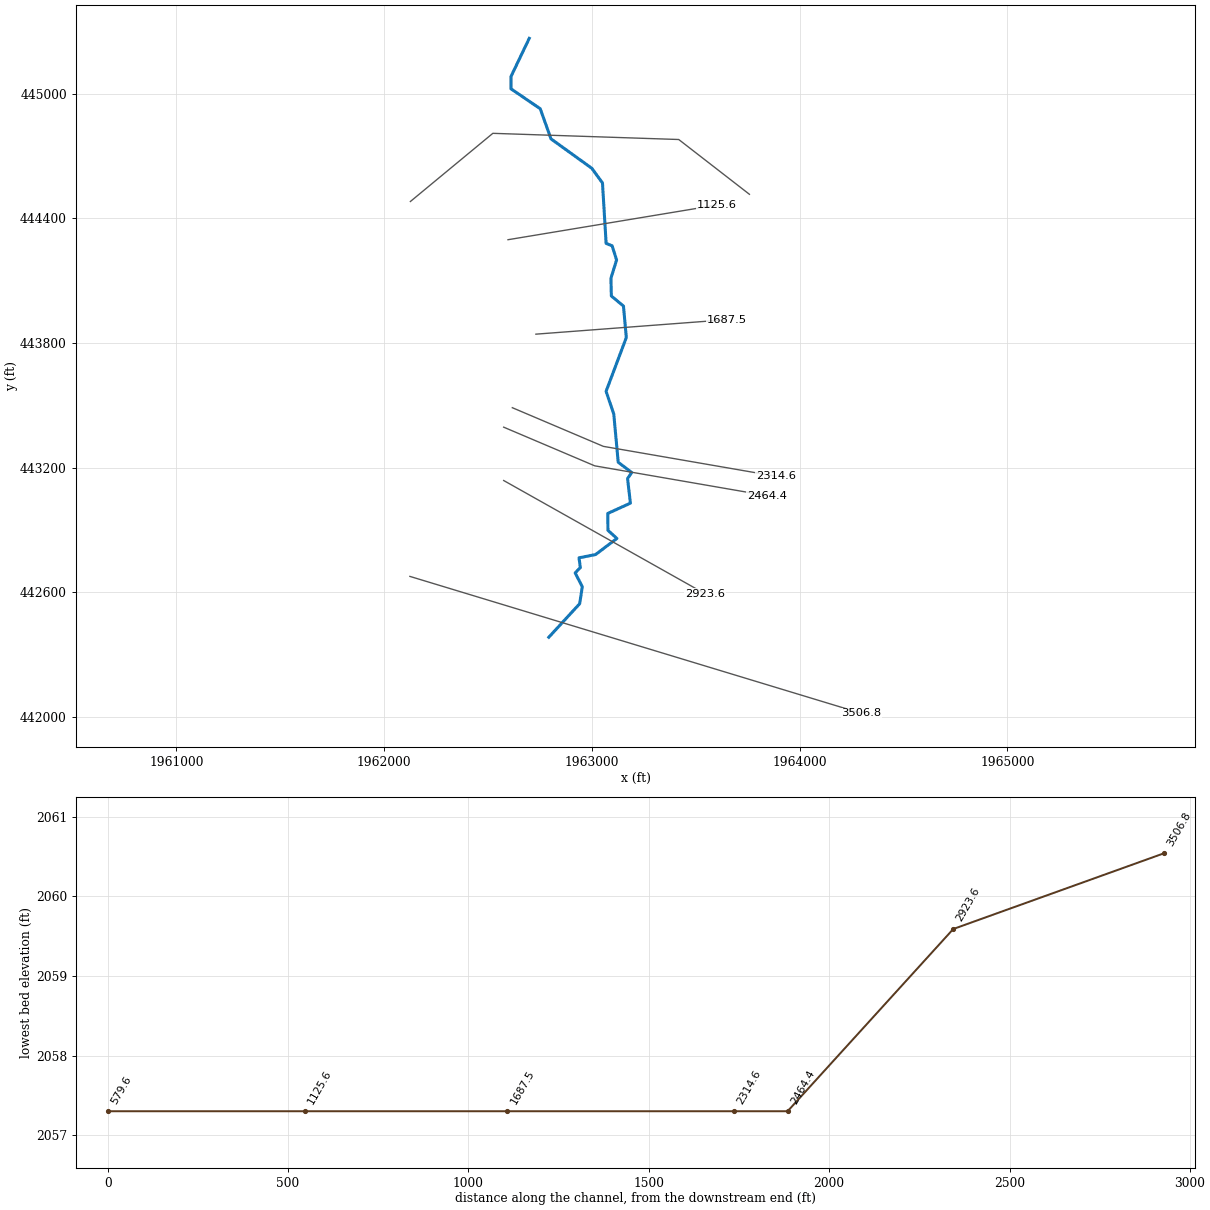
--- NP8.prj (project) ---

Proj Title=NP8
Current Plan=p01
Default Exp/Contr=0,0
English Units
Geom File=g01
Flow File=f01
Plan File=p01
BEGIN DESCRIPTION:
END DESCRIPTION:
DSS Export Rating Curves= 0
DSS Export Rating Curve Sorted= 0
DSS Export Volume Flow Curves= 0
DXF OffsetX= 0
DXF OffsetY= 0
DXF ScaleX= 0
DXF ScaleY= 0

--- NP8.p01 (plan) ---

Plan Title=Floodplain
Program Version=4.00
Geom File=g01
Flow File=f01
K Sum by GR=0
Std Step Tol=0.01
Critical Tol=0.01
Num of Std Step Trials=20
Max Error Tol=0.3
Flow Tol Ratio=0.001
Split Flow NTrial=30
Split Flow Tol=0.02
Split Flow Ratio=0.02
Log Output Level=0
Friction Slope Method=1
Unsteady Friction Slope Method=2
Unsteady Bridges Friction Slope Method=1
Global Log Level=0
CheckData=False
Run HTab=0
Run UNet=0
Run PostProcess=0
UNET Theta=0
UNET Theta Warmup=0
UNET ZTol=0
UNET ZSATol=0
UNET MxIter=0
UNET MaxInSteps=0
UNET DtIC=0
UNET DtMin=0
UNET MaxCRTS=0
UNET WFStab=0
UNET SFStab=0
UNET WFX=0
UNET SFX=0
UNET DSS MLevel=0
UNET DZMax Abort=0
UNET Convert EG Bridges=0
UNET Use Existing IB Tables=0
UNET Froude Limit=0
UNET Froude Power=0
Write IC File=0
Echo Input=False
Echo Output=False
Write Detailed=0

--- NP8.f01 (steady flow) ---

Flow Title=NFF Regression Equation
Program Version=4.10
Number of Profiles= 1
Profile Names=P100yr
River Rch & RM=NP8,Main            ,3506.8
517.7605
River Rch & RM=NP8,Main            ,579.6
554.4066
Boundary for River Rch & Prof#=NP8,Main            , 1
Up Type= 0
Dn Type= 3
Dn Slope=0.005
DSS Import GetInterval= 0
DSS Import GetPeak= 0
DSS Import FillOption= 0

--- NP8.g01 (geometry) ---

Geom Title=USGS 10m DEM
Program Version=4.10

River Reach=NP8             ,Main
Reach XY= 30
     1962792.174      442382.802      1962940.77      442544.264
     1962953.344      442625.995      1962919.14      442692.868
     1962943.914      442718.203     1962937.626      442765.355
     1963017.261      442781.072     1963119.948      442858.611
     1963076.987      442897.381     1963075.939      442979.111
     1963184.913      443028.568     1963171.291      443146.972
       1963191.2      443176.311     1963126.235      443225.559
     1963104.875      443458.013     1963067.886      443567.033
     1963165.224      443825.954     1963151.597      443977.802
     1963093.194      444026.471     1963091.247      444112.129
     1963118.502      444199.735     1963097.087      444267.872
     1963068.049      444279.807     1963050.541      444570.673
     1962999.022      444641.512     1962802.605      444783.189
     1962751.086      444928.087     1962609.957      445024.292
     1962610.139      445083.349     1962698.147      445267.298

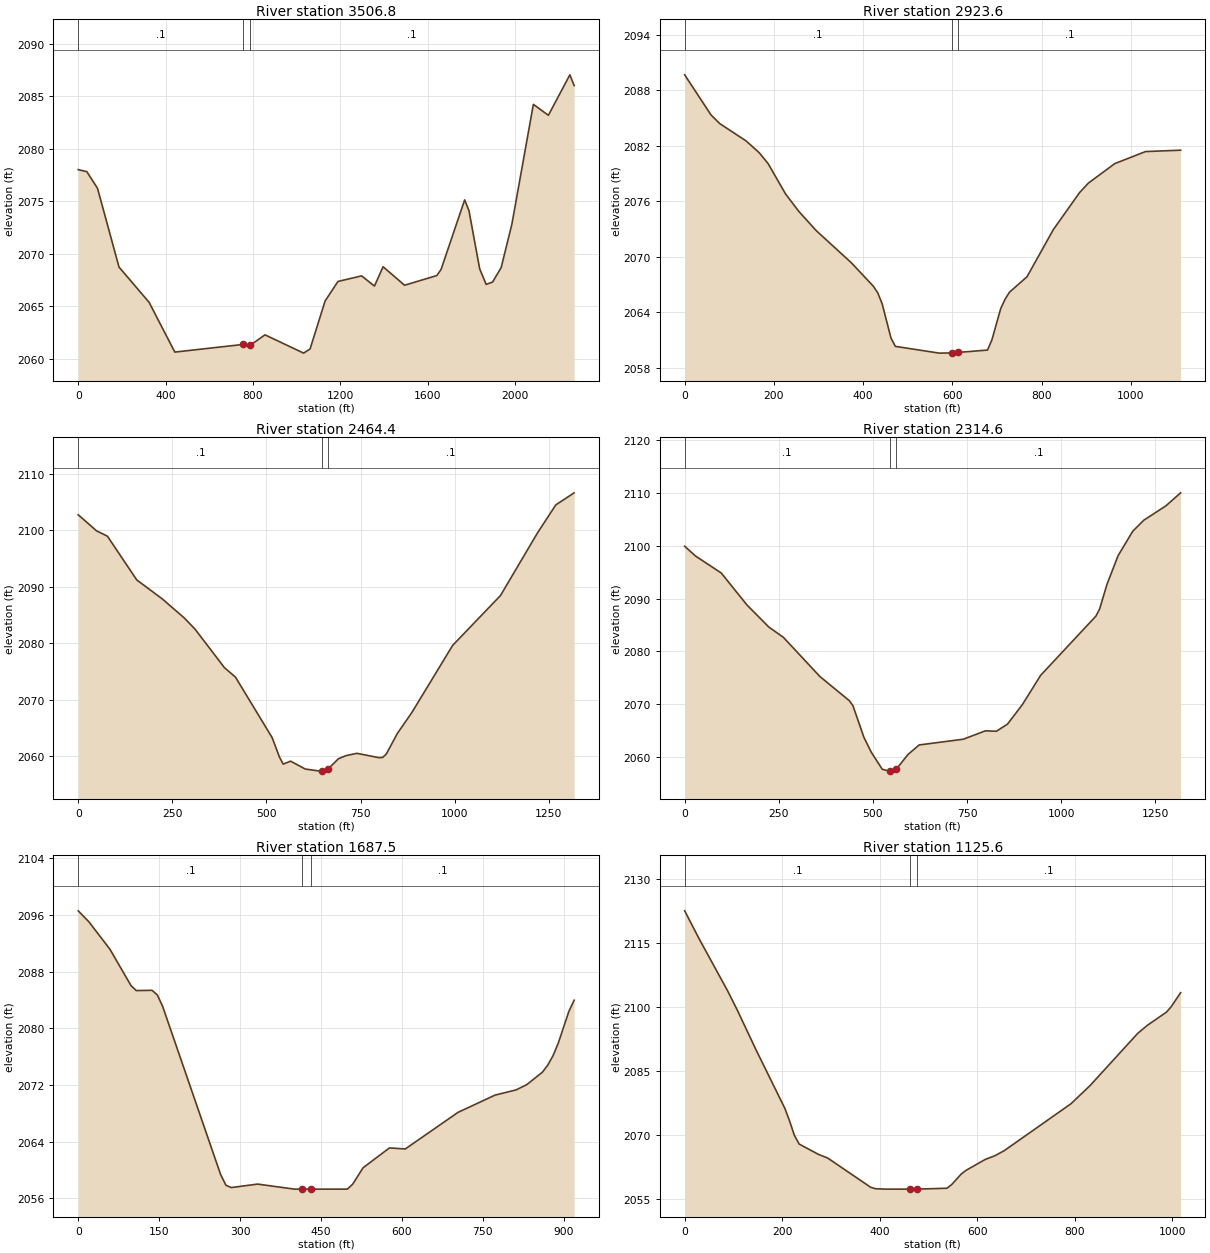
Type RM Length L Ch R = 1 ,3506.8  ,586.5,583.2,566.7
XS GIS Cut Line= 2
     1962123.569      442675.862      1964297.18       442016.14
#Sta/Elev= 30
       0    2078    39.3 2077.81    88.5 2076.22   186.8 2068.73   324.5 2065.38
   442.5 2060.64     757 2061.37   786.7 2061.27   855.5 2062.28  1032.5 2060.54
    1062 2060.94  1130.8  2065.5  1189.8 2067.36    1298 2067.89    1357 2066.92
  1396.4 2068.76  1494.7    2067  1642.2 2067.92  1661.8 2068.49    1770 2075.12
  1789.7  2074.1  1838.8 2068.56  1868.4 2067.08  1897.8  2067.3  1937.2 2068.68
  1986.4 2072.82  2084.7 2084.21  2153.5 2083.17  2251.9 2087.02  2271.5    2086
#Mann= 3 , 0 , 0
       0      .1       0     757    .045       0   786.7      .1       0
Bank Sta=757,786.7
XS Rating Curve= 0 ,0
Exp/Cntr=0.3,0.1

Type RM Length L Ch R = 1 ,2923.6  ,435.2,459.2,466.6
XS GIS Cut Line= 2
     1962574.958      443137.668     1963543.708      442592.529
#Sta/Elev= 30
       0 2089.65      59 2085.32    78.7 2084.38   137.7 2082.51   167.2 2081.23
   186.9 2080.07   226.2 2076.78   255.8  2074.9   295.1 2072.81   373.8 2069.34
     423 2066.81   432.8  2066.1   442.7 2064.91   462.4 2061.22   472.2 2060.32
   570.6 2059.59   598.6 2059.61   613.6 2059.67   678.8 2059.92   688.6 2061.02
   708.3 2064.39   718.1 2065.41     728 2066.17   767.3 2067.84   826.3 2072.93
   885.3 2076.94     905 2077.96     964 2080.06  1032.9 2081.36  1111.6 2081.51
#Mann= 3 , 0 , 0
       0      .1       0   598.6    .045       0   613.6      .1       0
Bank Sta=598.6,613.6
XS Rating Curve= 0 ,0
Exp/Cntr=0.3,0.1

Type RM Length L Ch R = 1 ,2464.4  ,141.3,149.8,149.4
XS GIS Cut Line= 3
     1962574.958      443394.612     1963013.122      443208.389
     1963842.319      443064.751
#Sta/Elev= 30
       0 2102.79    48.6 2099.94    77.7 2098.98   155.5 2091.23   223.5 2087.85
   281.8 2084.48   310.9 2082.45   388.6 2075.65   417.8 2073.98   515.2 2063.25
   534.8 2059.77   544.6 2058.55   564.2 2059.07   603.3 2057.67   642.4  2057.3
     649 2057.31     664 2057.69   691.4  2059.5     711 2060.04   740.3 2060.46
     799 2059.69   808.8 2059.73   818.6 2060.34   847.9 2063.98   887.1 2067.77
   994.7  2079.6  1121.9 2088.46  1219.8 2099.52  1268.7 2104.53  1317.6 2106.68
#Mann= 3 , 0 , 0
       0      .1       0     649    .045       0     664      .1       0
Bank Sta=649,664
XS Rating Curve= 0 ,0
Exp/Cntr=0.3,0.1

Type RM Length L Ch R = 1 ,2314.6  ,621.2,627.1,632.7
XS GIS Cut Line= 3
     1962616.625      443488.362     1963054.788      443302.139
     1963883.986      443158.501
#Sta/Elev= 30
       0 2099.93    29.2 2098.06    97.2 2094.86   165.2 2088.82   223.5 2084.62
   262.3 2082.66   359.5 2075.22   437.2 2070.67     447 2069.71   476.1 2063.73
   495.7 2060.89     525 2057.65   544.6  2057.3   561.8 2057.63   593.5 2060.47
   622.9 2062.26   740.3 2063.35     799 2064.94   828.4 2064.86   857.7 2066.22
   896.9 2069.88   945.8 2075.47  1092.6 2086.69  1102.4 2088.04  1121.9  2092.7
  1151.3 2098.12  1190.4 2102.78  1219.8 2104.87  1278.5 2107.59  1317.6 2110.06
#Mann= 3 , 0 , 0
       0      .1       0   544.6    .045       0   561.8      .1       0
Bank Sta=544.6,561.8
XS Rating Curve= 0 ,0
Exp/Cntr=0.3,0.1

Type RM Length L Ch R = 1 ,1687.5  ,562.5,561.9,557.2
XS GIS Cut Line= 2
     1962730.051      443842.529     1963646.717      443911.973
#Sta/Elev= 30
       0 2096.59    19.6 2095.06    58.7 2091.18    97.8 2086.04   107.6 2085.33
   136.9 2085.37   146.7 2084.71   156.5  2083.1     264 2059.36   273.8 2057.85
   283.6 2057.52   332.5 2058.01     401  2057.3   415.7  2057.3   430.7  2057.3
   498.8  2057.3   508.6 2057.98   528.1 2060.32     577 2063.12   606.3 2062.97
   704.1 2068.14   772.6 2070.57   811.7 2071.31   831.3 2072.04   860.6 2073.82
   870.4 2074.81   880.2 2076.14     890 2077.94   909.5 2082.39   919.3 2083.97
#Mann= 3 , 0 , 0
       0      .1       0   415.7    .045       0   430.7      .1       0
Bank Sta=415.7,430.7
XS Rating Curve= 0 ,0
Exp/Cntr=0.3,0.1

Type RM Length L Ch R = 1 ,1125.6  ,550.4,546,541.6
XS GIS Cut Line= 2
     1962595.791       444297.39     1963599.264      444464.057
#Sta/Elev= 30
       0  2122.5    29.3 2116.02      88 2103.77   107.6 2099.32   146.7 2089.85
   205.4 2076.24   215.2 2073.26     225 2069.91   234.7 2067.87   273.9 2065.47
   293.4 2064.58   381.5 2057.73   391.2  2057.4   410.8  2057.3   462.2  2057.3
   477.2  2057.3     538 2057.51   547.7 2058.38   567.3 2060.84   577.1  2061.7
   616.2 2064.24   635.8  2065.1   655.3  2066.3   792.3  2077.3   831.4 2081.55
   929.2 2093.79   948.8 2095.66   987.9 2098.75   997.7 2100.01  1017.2 2103.32
#Mann= 3 , 0 , 0
       0      .1       0   462.2    .045       0   477.2      .1       0
Bank Sta=462.2,477.2
XS Rating Curve= 0 ,0
Exp/Cntr=0.3,0.1

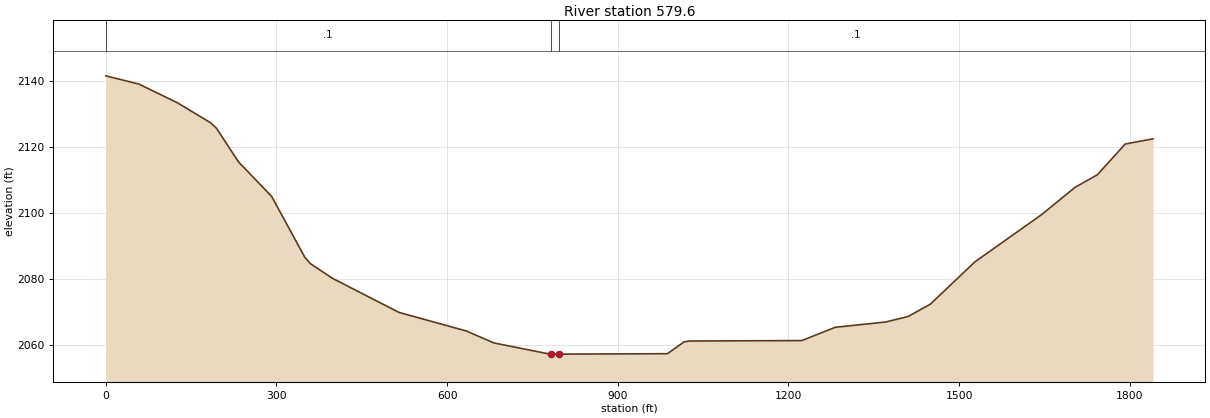
Type RM Length L Ch R = 1 ,579.6   ,522.3,521.5,520.6
XS GIS Cut Line= 4
     1962125.884      444481.418     1962522.858      444809.795
     1963417.551      444780.029     1963757.828       444516.14
#Sta/Elev= 30
       0 2141.49    58.3 2138.99   126.4  2133.3   184.7 2127.23   194.4 2125.69
   233.3 2115.46   291.6    2105   349.9 2086.61   359.7 2084.67   398.5 2080.24
   515.2 2069.93   633.2 2064.33   682.4 2060.68   780.8  2057.3   782.1  2057.3
   797.1  2057.3   987.4 2057.43  1016.9 2061.04  1026.7 2061.27  1223.5  2061.4
  1282.5 2065.42    1371 2067.02  1410.4 2068.68  1449.5 2072.42  1527.8  2085.2
  1645.3 2099.53    1704 2107.77  1743.1 2111.56  1792.1 2120.86    1841 2122.44
#Mann= 3 , 0 , 0
       0      .1       0   782.1    .045       0   797.1      .1       0
Bank Sta=782.1,797.1
XS Rating Curve= 0 ,0
Exp/Cntr=0.3,0.1

Chan Stop Cuts=-1
Use User Specified Reach Order=0
Composite Channel Slope=5